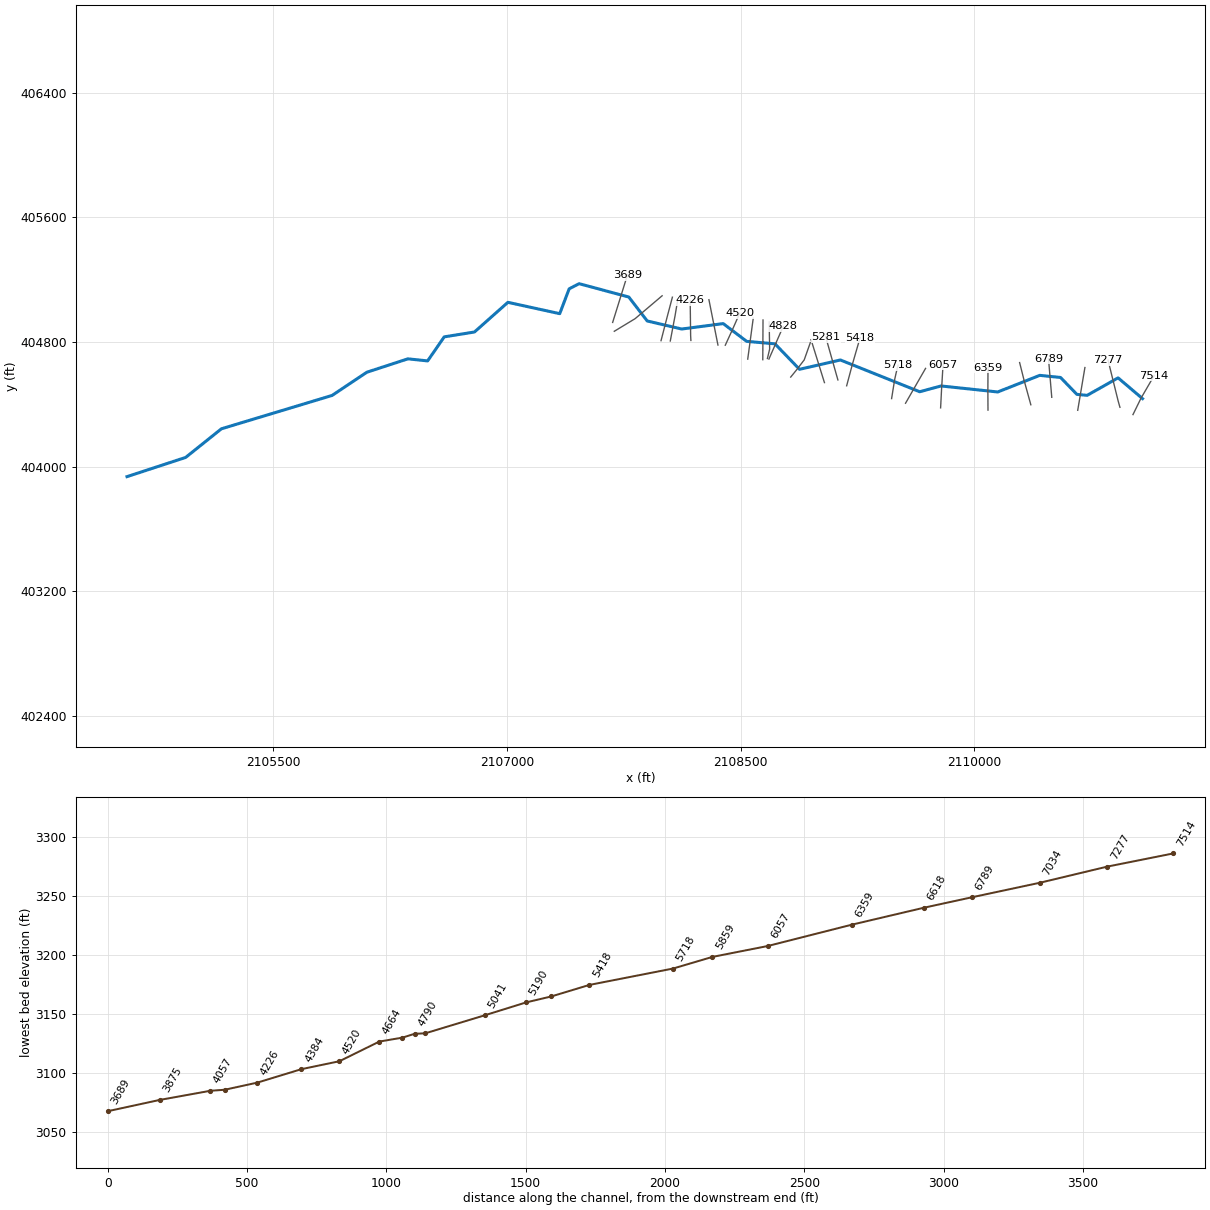
--- COLDSPRBR.prj (project) ---

Proj Title=COLDSPRBR
Current Plan=p01
Default Exp/Contr=0.3,0.1
English Units
Geom File=g01
Flow File=f01
Plan File=p01
Y Axis Title=Elevation
X Axis Title(PF)=Main Channel Distance
X Axis Title(XS)=Station
BEGIN DESCRIPTION:
Stream Name- Cold Spring Branch
Flood Zone: Zone A
Greenbrier County, WV
County-Wide Study
WVDHSEM-2018-3, Flood Risk Project
HEC-RAS Version: 5.0.7
General Notes:
For the Hydrology regression was used.
END DESCRIPTION:
DSS Export Rating Curves= 0
DSS Export Rating Curve Sorted= 0
DSS Export Volume Flow Curves= 0
DXF Filename=COLDSPRBR.M2.
DXF OffsetX= 0
DXF OffsetY= 0
DXF ScaleX= 1
DXF ScaleY= 10

--- COLDSPRBR.p01 (plan) ---

Plan Title=Floodplain
Program Version=5.07
Short Identifier=Floodplain
Geom File=g01
Flow File=f01
Subcritical Flow
K Sum by GR= 0
Std Step Tol= 0.01
Critical Tol= 0.01
Num of Std Step Trials= 20
Max Error Tol= 0.3
Flow Tol Ratio= 0.001
Split Flow NTrial= 30
Split Flow Tol= 0.02
Split Flow Ratio= 0.02
Log Output Level= 0
Friction Slope Method= 1
Unsteady Friction Slope Method= 2
Unsteady Bridges Friction Slope Method= 1
Parabolic Critical Depth
Global Vel Dist= 0 , 0 , 0
Global Log Level= 0
CheckData=True
Encroach Param=-1 ,0,0, 0
Computation Interval=1MIN
Output Interval=1HOUR
Instantaneous Interval=1HOUR
Mapping Interval=1HOUR
Computation Time Step Use Courant=        0
Computation Time Step Use Time Series=    0
Computation Time Step Count To Double=0
Computation Time Step Max Doubling=0
Computation Time Step Max Halving=0
Computation Time Step Residence Courant=0
Run HTab= 0
Run UNet= 0
Run Sediment= 0
Run PostProcess= 0
Run WQNet= 0
Run RASMapper= 0
UNET Theta= 1
UNET Theta Warmup= 1
UNET ZTol= 0.02
UNET ZSATol= 0.02
UNET MxIter= 20
UNET Max Iter WO Improvement= 0
UNET MaxInSteps= 0
UNET DtIC= 0
UNET DtMin= 0
UNET MaxCRTS= 20
UNET WFStab= 2
UNET SFStab= 1
UNET WFX= 1
UNET SFX= 1
UNET 1D Methodology=Finite Difference
UNET DSS MLevel= 4
UNET Pardiso=0
UNET DZMax Abort= 100
UNET Use Existing IB Tables=-1
UNET Froude Reduction=False
UNET Froude Limit= 0.8
UNET Froude Power= 4
UNET D1 Cores= 0
UNET D2 Coriolis=0
UNET D2 Cores= 0
UNET D2 Theta= 1
UNET D2 Theta Warmup= 1
UNET D2 Z Tol= 0.01
UNET D2 Volume Tol= 0.01
UNET D2 Max Iterations= 20
UNET D2 Equation= 0
UNET D2 RampUpFraction=0.1
UNET D2 TimeSlices= 1
UNET D2 BCVolumeCheck=0
UNET D1D2 MaxIter= 0
UNET D1D2 ZTol=0.01
UNET D1D2 QTol=0.1
UNET D1D2 MinQTol=1
Write IC File= 0
Write IC File at Fixed DateTime=0
Write IC File at Sim End=0
Echo Input=False
Echo Parameters=False
Echo Output=False
Write Detailed= 0
HDF Write Warmup=0
HDF Write Time Slices=0
HDF Flush=0
HDF Face Node Velocities=0
HDF Compression= 1
HDF Chunk Size= 1
HDF Spatial Parts= 1
HDF Use Max Rows=0
HDF Fixed Rows= 1
Calibration Method= 0
Calibration Iterations= 20
Calibration Max Change=0.05
Calibration Tolerance=0.2
Calibration Maximum=1.5
Calibration Minimum=0.5
Calibration Optimization Method= 1
WQ AD Non Conservative
WQ ULTIMATE=-1
WQ Max Comp Step=1HOUR
WQ Output Interval=15MIN
WQ Output Selected Increments= 0
WQ Output face flow=0
WQ Output face velocity=0
WQ Output face area=0
WQ Output face dispersion=0
WQ Output cell volume=0
WQ Output cell surface area=0
WQ Output cell continuity=0
WQ Output cumulative cell continuity=0
WQ Output face conc=0
WQ Output face dconc_dx=0
WQ Output face courant=0
WQ Output face peclet=0
WQ Output face adv mass=0
WQ Output face disp mass=0
WQ Output cell mass=0
WQ Output cell source sink temp=0
WQ Output nsm pathways=0
WQ Output nsm derived pathways=0
WQ Output MaxMinRange=-1
WQ Daily Max Min Mean=-1
WQ Daily Range=0
WQ Daily Time=0
WQ Create Restart=0
WQ Fixed Restart=0
WQ System Summary=0
WQ Write To DSS=0
WQ Use Fixed Temperature=0
Sorting and Armoring Iterations= 10
XS Update Threshold= 0.02
Bed Roughness Predictor= 0
Hydraulics Update Threshold= 0.02
Energy Slope Method= 1
Volume Change Method= 1
Sediment Retention Method= 0
XS Weighting Method= 0
Number of US Weighted Cross Sections= 1
Number of DS Weighted Cross Sections= 1
Upstream XS Weight=0
Main XS Weight=1
Downstream XS Weight=0
Number of DS XS's Weighted with US Boundary= 1
Upstream Boundary Weight= 1
Weight of XSs Associated with US Boundary= 0
Number of US XS's Weighted with DS Boundary= 1
Downstream Boundary Weight= 0.5
Weight of XSs Associated with DS Boundary= 0.5
Percentile Method= 0
Sediment Output Level= 3
Mass or Volume Output= 0
Output Increment Type= 1
Profile and TS Output Increment= 1
XS Output Flag= 0
XS Output Increment= 10
Write Gradation File= 0
Read Gradation Hotstart= 0
Write HDF5 File= 1
Write Binary Output= 1
Write DSS Sediment File= 0
SV Curve= 0
Specific Gage Flag= 0

--- COLDSPRBR.f01 (steady flow) ---

Flow Title=Flow
Program Version=5.07
Number of Profiles= 6
Profile Names=f1p,f10p,f4p,f2p,f02p,f1pplus
River Rch & RM=COLDSPRBR,Main            ,7514
     515     271     361     436     721     762
River Rch & RM=COLDSPRBR,Main            ,7034
     574     303     403     486     802     849
River Rch & RM=COLDSPRBR,Main            ,2967
     657     349     463     557     916     972
River Rch & RM=COLDSPRBR,Main            ,1721
     734     392     518     623    1020    1090
Boundary for River Rch & Prof#=BEECHRN1,Main            , 1
Up Type= 0
Dn Type= 3
Dn Slope=0.035
Boundary for River Rch & Prof#=BEECHRN1,Main            , 2
Up Type= 0
Dn Type= 3
Dn Slope=0.035
Boundary for River Rch & Prof#=BEECHRN1,Main            , 3
Up Type= 0
Dn Type= 3
Dn Slope=0.035
Boundary for River Rch & Prof#=BEECHRN1,Main            , 4
Up Type= 0
Dn Type= 3
Dn Slope=0.035
Boundary for River Rch & Prof#=BEECHRN1,Main            , 5
Up Type= 0
Dn Type= 3
Dn Slope=0.035
Boundary for River Rch & Prof#=BEECHRN1,Main            , 6
Up Type= 0
Dn Type= 3
Dn Slope=0.035
Boundary for River Rch & Prof#=COLDSPRBR,Main            , 1
Up Type= 0
Dn Type= 3
Dn Slope=0.036398
Boundary for River Rch & Prof#=COLDSPRBR,Main            , 2
Up Type= 0
Dn Type= 3
Dn Slope=0.036398
Boundary for River Rch & Prof#=COLDSPRBR,Main            , 3
Up Type= 0
Dn Type= 3
Dn Slope=0.036398
Boundary for River Rch & Prof#=COLDSPRBR,Main            , 4
Up Type= 0
Dn Type= 3
Dn Slope=0.036398
Boundary for River Rch & Prof#=COLDSPRBR,Main            , 5
Up Type= 0
Dn Type= 3
Dn Slope=0.036398
Boundary for River Rch & Prof#=COLDSPRBR,Main            , 6
Up Type= 0
Dn Type= 3
Dn Slope=0.036398
Boundary for River Rch & Prof#=HOGCMPRN,Main            , 1
Up Type= 0
Dn Type= 3
Dn Slope=0.02
Boundary for River Rch & Prof#=HOGCMPRN,Main            , 2
Up Type= 0
Dn Type= 3
Dn Slope=0.02
Boundary for River Rch & Prof#=HOGCMPRN,Main            , 3
Up Type= 0
Dn Type= 3
Dn Slope=0.02
Boundary for River Rch & Prof#=HOGCMPRN,Main            , 4
Up Type= 0
Dn Type= 3
Dn Slope=0.02
Boundary for River Rch & Prof#=HOGCMPRN,Main            , 5
Up Type= 0
Dn Type= 3
Dn Slope=0.02
Boundary for River Rch & Prof#=HOGCMPRN,Main            , 6
Up Type= 0
Dn Type= 3
Dn Slope=0.02
Boundary for River Rch & Prof#=JOBKNOBBR2,Main            , 1
Up Type= 0
Dn Type= 3
Dn Slope=0.043277
Boundary for River Rch & Prof#=JOBKNOBBR2,Main            , 2
Up Type= 0
Dn Type= 3
Dn Slope=0.043277
Boundary for River Rch & Prof#=JOBKNOBBR2,Main            , 3
Up Type= 0
Dn Type= 3
Dn Slope=0.043277
Boundary for River Rch & Prof#=JOBKNOBBR2,Main            , 4
Up Type= 0
Dn Type= 3
Dn Slope=0.043277
Boundary for River Rch & Prof#=JOBKNOBBR2,Main            , 5
Up Type= 0
Dn Type= 3
Dn Slope=0.043277
Boundary for River Rch & Prof#=JOBKNOBBR2,Main            , 6
Up Type= 0
Dn Type= 3
Dn Slope=0.043277
Boundary for River Rch & Prof#=MCMILLCK,Main            , 1
Up Type= 0
Dn Type= 3
Dn Slope=0.03585
Boundary for River Rch & Prof#=MCMILLCK,Main            , 2
Up Type= 0
Dn Type= 3
Dn Slope=0.03585
Boundary for River Rch & Prof#=MCMILLCK,Main            , 3
Up Type= 0
Dn Type= 3
Dn Slope=0.03585
Boundary for River Rch & Prof#=MCMILLCK,Main            , 4
Up Type= 0
Dn Type= 3
Dn Slope=0.03585
Boundary for River Rch & Prof#=MCMILLCK,Main            , 5
Up Type= 0
Dn Type= 3
Dn Slope=0.03585
Boundary for River Rch & Prof#=MCMILLCK,Main            , 6
Up Type= 0
Dn Type= 3
Dn Slope=0.03585
Boundary for River Rch & Prof#=MIDDLEBR,Main            , 1
Up Type= 0
Dn Type= 3
Dn Slope=0.083839
Boundary for River Rch & Prof#=MIDDLEBR,Main            , 2
Up Type= 0
Dn Type= 3
Dn Slope=0.083839
Boundary for River Rch & Prof#=MIDDLEBR,Main            , 3
Up Type= 0
Dn Type= 3
Dn Slope=0.083839
Boundary for River Rch & Prof#=MIDDLEBR,Main            , 4
Up Type= 0
Dn Type= 3
Dn Slope=0.083839
Boundary for River Rch & Prof#=MIDDLEBR,Main            , 5
Up Type= 0
Dn Type= 3
Dn Slope=0.083839
Boundary for River Rch & Prof#=MIDDLEBR,Main            , 6
Up Type= 0
Dn Type= 3
Dn Slope=0.083839
DSS Import GetInterval= 0
DSS Import GetPeak= 0
DSS Import FillOption= 0

--- COLDSPRBR.g01 (geometry) ---

Geom Title=Geometry
Program Version=5.07

River Reach=COLDSPRBR       ,Main
Reach XY= 30
2111078.98684835404435.6589799672110922.04687351 404569.07505171
2110723.67916003404456.8151056322110657.64320287404463.026707381
2110552.63389844404571.544206873 2110419.3005037404585.085846454
2110149.50904852404478.488618717 2109785.6561017404517.014132217
2109648.21083853404479.9239832912109139.40706611404683.812026963
2108876.93941519  404623.97487632108719.30062285404787.516543955
 2108537.6484271404803.4193992912108387.09295395404917.308279127
2108120.42616445404882.5859076232107899.31505811404934.252470955
2107780.98163337405087.8637122962107462.09283543405173.697202042
 2107398.2038556405140.6414938722107337.55994803404981.128033385
2107004.87065277405053.9746724672106790.14831319404863.419279292
2106596.25959337 404832.308121042106489.59281194404677.863876134
2106362.92607051404691.197182789 2106099.0371626404605.085806459
2105876.25939295404456.1969966292105165.70405552404242.030430213
2104935.98174593404058.1413622952104559.74201286403934.944758296

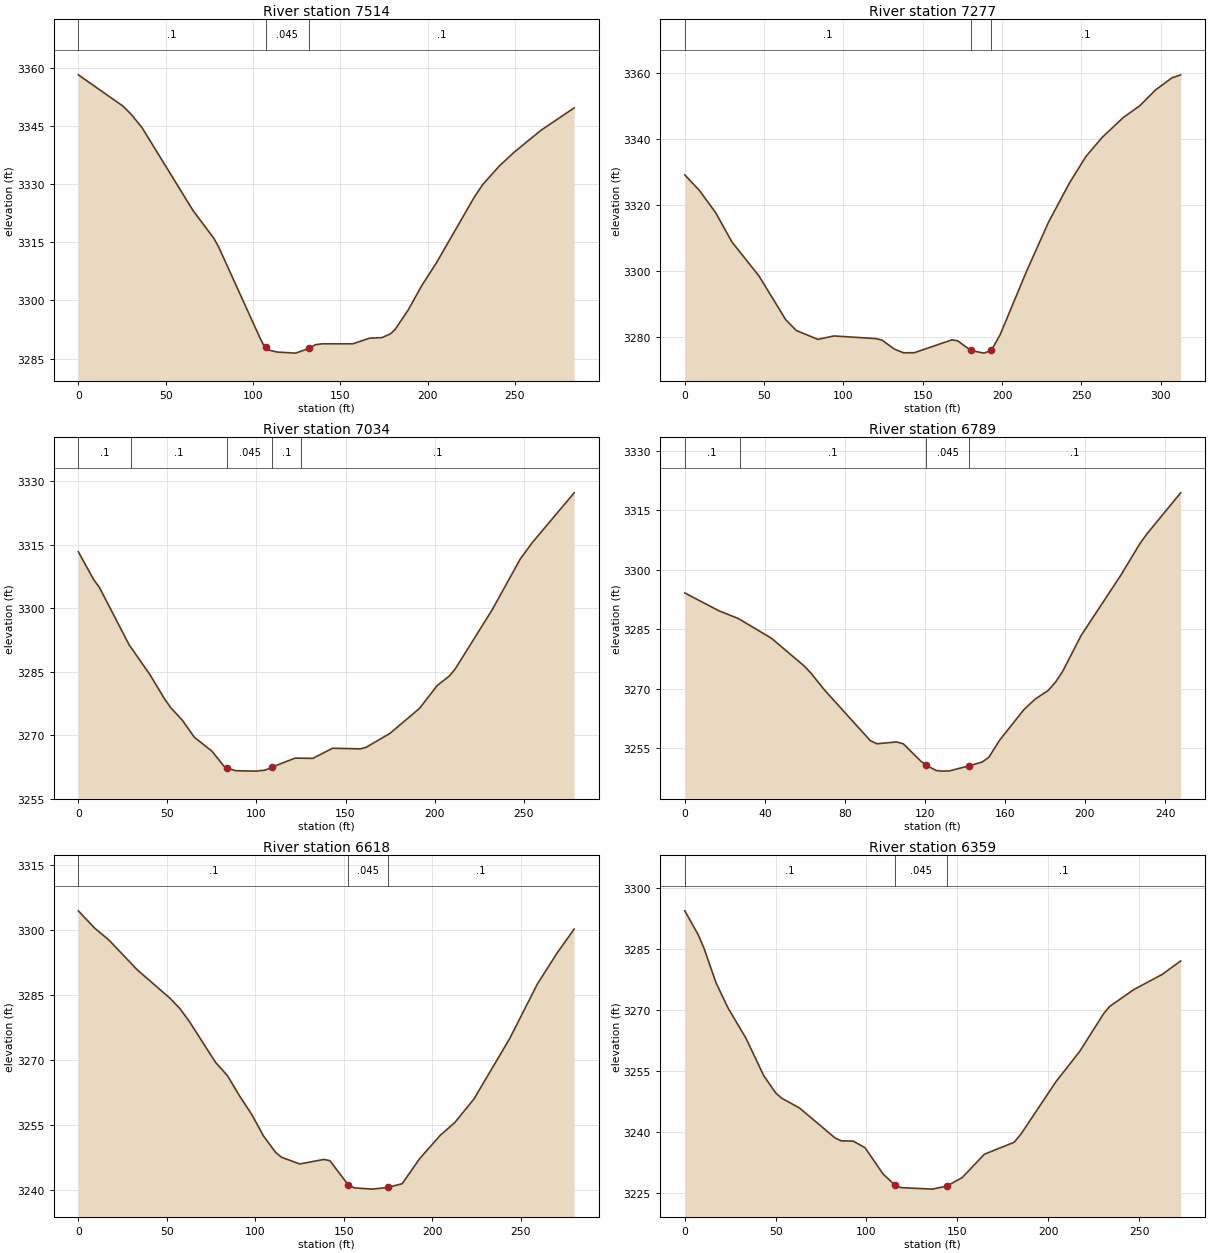
Type RM Length L Ch R = 1 ,7514    ,229.8,236.7,237.4
XS GIS Cut Line= 3
2111017.68414944404333.2339879572111069.93798193404439.911924213
2111153.03624094404582.552386954
#Sta/Elev= 30
       0 3358.21    25.5 3350.16    30.4 3347.96    36.5 3344.57    65.8 3323.11
    77.6 3316.05    80.4 3313.75     104 3290.35   105.9 3288.65   107.4 3287.97
   109.6 3287.16   113.8  3286.7   124.4 3286.42     132 3287.64   135.8  3288.6
   139.6 3288.82   157.1 3288.82   166.7 3290.27   173.9 3290.43   178.7 3291.38
   181.4 3292.54     189 3297.63   196.6 3303.81   205.1 3309.76   226.6 3326.57
   231.4 3329.82     241 3334.67   249.7 3338.31     265 3343.93   283.9 3349.68
#Mann= 3 ,-1 , 0
       0      .1       0   107.4    .045       0     132      .1       0
Bank Sta=107.4,132
XS Rating Curve= 0 ,0
Exp/Cntr=0.3,0.1

Type RM Length L Ch R = 1 ,7277    ,249.8,242.7,236.4
XS GIS Cut Line= 3
 2110933.9389101404380.1216894542110922.65415576404420.052383885
2110857.54995528404683.073183298
#Sta/Elev= 30
       0 3329.22     9.2 3324.52    19.5 3317.74    29.7 3308.92    46.7 3298.65
    63.6 3285.39    70.3 3282.09    83.9 3279.42      94 3280.45   120.5 3279.65
   124.4 3279.17   132.1 3276.46   137.9 3275.35   144.7 3275.38   168.4 3279.27
     172 3278.97   180.3 3276.05   188.6 3275.25  193.243276.126   198.8 3280.89
   215.3 3299.93   229.2 3314.86   242.4 3326.73   252.9 3334.85     263 3340.55
   276.5 3346.65   286.7 3350.12   296.6  3354.9   306.9 3358.57   312.5 3359.52
#Mann= 3 ,-1 , 0
       0      .1       0   180.3    .045       0  193.24      .1       0
Bank Sta=180.3,193.24
XS Rating Curve= 0 ,0
Exp/Cntr=0.3,0.1

Type RM Length L Ch R = 1 ,7034    ,239.3,245.2,243.8
XS GIS Cut Line= 2
2110662.93190619404360.8943657132110709.11258811404635.330168545
#Sta/Elev= 30
       0 3313.36     8.5 3306.85    11.9 3304.87    28.5 3291.38    40.2 3284.31
    48.5 3278.52    51.8 3276.55    58.4 3273.53    65.1 3269.53    75.1  3266.2
    81.7 3262.69   83.66 3262.21    88.4 3261.61    99.9 3261.52     105 3261.76
   108.5 3262.44   121.7  3264.6   131.6 3264.53   142.7 3266.93   158.3 3266.78
   161.6 3267.17   174.9 3270.43   191.5 3276.35   201.5 3281.78   208.2 3283.97
   211.5 3285.64   232.2 3299.58   248.1 3311.67   254.7 3315.47   278.3 3327.28
#Mann= 5 ,-1 , 0
       0      .1       0    29.3      .1       0   83.66    .045       0
   108.5      .1       0  125.22      .1       0
Bank Sta=83.66,108.5
XS Rating Curve= 0 ,0
Exp/Cntr=0.3,0.1

Type RM Length L Ch R = 1 ,6789    ,168.4,171.3,172.3
XS GIS Cut Line= 2
2110496.26524478404444.227860466 2110475.4319531404691.102694795
#Sta/Elev= 30
       0 3294.16      17 3289.66    26.9 3287.66    43.4 3282.67    59.8 3275.65
    63.1 3273.87    69.7  3269.7    92.7 3256.84      96 3256.05   105.8  3256.5
   109.2 3256.04   117.9 3251.68  120.763250.587   125.7 3249.27     129 3249.13
   132.3  3249.2   142.2 3250.48   148.7 3251.46     152 3252.65   157.4 3256.99
   169.5 3264.68   175.1 3267.33   181.6 3269.51   185.2 3271.56   188.8 3274.29
   198.1 3283.44   217.9 3298.63   227.7 3306.82     231  3309.1   247.8 3319.46
#Mann= 4 ,-1 , 0
       0      .1       0   27.39      .1       0  120.76    .045       0
   142.2      .1       0
Bank Sta=120.76,142.2
XS Rating Curve= 0 ,0
Exp/Cntr=0.3,0.1

Type RM Length L Ch R = 1 ,6618    ,261,258.7,254.6
XS GIS Cut Line= 3
2110361.89018545404396.310961545 2110318.2590391404554.562941626
2110290.01532918404667.144409373
#Sta/Elev= 30
       0  3304.5     9.3 3300.49    17.3 3297.76    33.3 3290.89      52 3284.27
    57.3 3281.99    62.7 3279.01    77.5 3269.57    84.3 3266.47    91.1 3261.81
    97.9  3257.6   104.7 3252.53   111.5 3248.78   114.9 3247.64   125.1 3246.12
   138.8 3247.16   142.2 3246.86  152.673241.217   155.8 3240.61     166 3240.31
   174.8 3240.69     183 3241.56     193  3247.4   204.6 3252.76   212.7 3255.65
   223.5 3261.06   243.8 3275.06   259.5 3287.69   270.8 3294.91   280.2 3300.29
#Mann= 3 ,-1 , 0
       0      .1       0  152.67    .045       0   174.8      .1       0
Bank Sta=152.67,174.8
XS Rating Curve= 0 ,0
Exp/Cntr=0.3,0.1

Type RM Length L Ch R = 1 ,6359    ,302.6,302.1,301.4
XS GIS Cut Line= 3
2110086.89040735404361.9360302982110086.17026445404481.269781128
2110086.89040735404634.852807298
#Sta/Elev= 30
       0 3294.31     7.4 3288.43    10.7 3284.95    17.2 3276.62    23.8 3270.44
    33.6 3263.05    43.5 3253.77      50 3249.58    53.3 3248.27    63.2 3245.84
    82.8 3238.46    86.1 3237.79    92.7 3237.72    99.2  3236.1   109.1 3229.66
   115.7 3226.89   118.9 3226.29   136.3 3225.92   144.2 3226.67   152.7 3228.76
   164.9  3234.5   181.3 3237.44   185.3 3239.63   204.2 3252.27   217.4 3259.79
   230.5 3269.01   233.8  3270.8   246.9 3274.89   262.9 3278.72   272.9 3281.99
#Mann= 3 ,-1 , 0
       0      .1       0   115.7    .045       0   144.2      .1       0
Bank Sta=115.7,144.2
XS Rating Curve= 0 ,0
Exp/Cntr=0.3,0.1

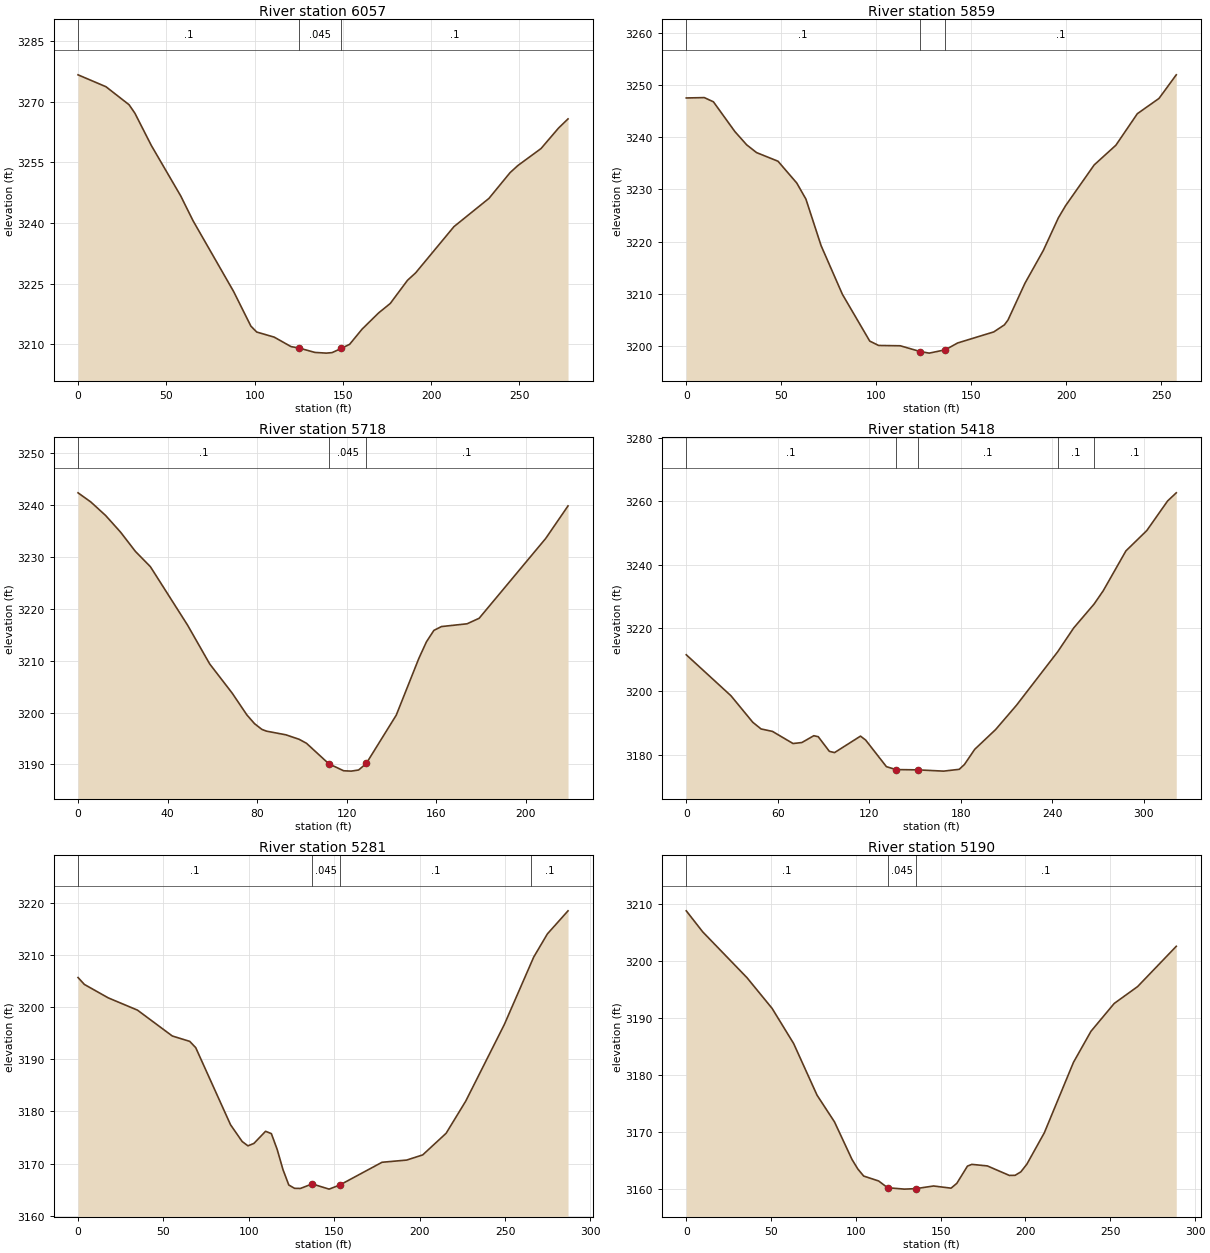
Type RM Length L Ch R = 1 ,6057    ,196.2,198.2,190.3
XS GIS Cut Line= 3
2109782.72369286404376.5193344652109788.63411412404490.984328628
 2109798.3486616404653.602769792
#Sta/Elev= 30
       0 3276.69    15.8 3273.75    28.9 3269.29    32.2 3267.19    41.5 3259.21
    58.2 3246.68    65.1  3240.6    88.1 3223.07    97.9 3214.49   101.2 3213.03
   111.1 3211.77   120.6 3209.43  125.273209.059   134.1 3207.99   140.6 3207.81
   143.9 3207.94   149.2    3209   153.8 3209.99   160.9 3213.76   170.2 3217.75
   176.8 3220.09   186.6 3225.84   191.2 3227.68   212.9 3239.12   232.7  3246.1
   244.7 3252.49   249.1 3254.24   262.2 3258.44   272.1  3263.5   277.5 3265.78
#Mann= 3 ,-1 , 0
       0      .1       0  125.27    .045       0   149.2      .1       0
Bank Sta=125.27,149.2
XS Rating Curve= 0 ,0
Exp/Cntr=0.3,0.1

Type RM Length L Ch R = 1 ,5859    ,138.9,141.1,143.7
XS GIS Cut Line= 2
2109557.56494889404406.1578721872109686.12399371404629.824373629
#Sta/Elev= 30
       0 3247.55     9.5 3247.62    14.3 3246.81    25.6  3241.1    31.8 3238.56
      37 3237.07    48.3 3235.41    58.2 3231.22      63 3228.14      71  3219.2
    82.2 3209.88    96.6  3200.9   101.3 3200.06   112.7    3200   123.1  3198.9
   127.9 3198.59   136.4 3199.23   142.9 3200.54   161.9 3202.66   167.5 3204.01
   169.4 3204.94   178.3 3211.98     188 3218.29   195.9 3224.53   199.7 3226.87
   214.8 3234.71   226.2 3238.48   237.5 3244.53   248.9 3247.46     258 3251.99
#Mann= 3 ,-1 , 0
       0      .1       0   123.1    .045       0   136.4      .1       0
Bank Sta=123.1,136.4
XS Rating Curve= 0 ,0
Exp/Cntr(USF)=0,0
Exp/Cntr=0.3,0.1

Type RM Length L Ch R = 1 ,5718    ,302.2,300,300.2
XS GIS Cut Line= 4
2109468.14033252404435.8945437972109487.69213068404557.846071541
2109498.34860545404605.6861989652109509.80691585404650.477776051
#Sta/Elev= 30
       0 3242.35     5.7 3240.59    12.3 3237.99      19 3234.77    25.6 3231.07
    32.3 3228.12    48.9 3216.86    58.8 3209.37    68.8 3203.77    75.4 3199.55
    78.8 3197.87    82.1 3196.76    84.2 3196.42    92.8 3195.72    98.7 3194.86
     102 3194.09     112 3190.13   118.6 3188.79     122 3188.72   125.3 3188.94
   128.7 3190.19   142.1 3199.51   152.2 3210.46   155.6 3213.66   158.9 3215.84
   162.3 3216.58   173.7 3217.11   179.1 3218.17   208.8 3233.54   218.8 3239.83
#Mann= 3 ,-1 , 0
       0      .1       0     112    .045       0   128.7      .1       0
Bank Sta=112,128.7
XS Rating Curve= 0 ,0
Exp/Cntr=0.3,0.1

Type RM Length L Ch R = 1 ,5418    ,135.7,136.3,144.3
XS GIS Cut Line= 3
2109179.59858677404518.1860458852109216.96498185404658.155910298
2109266.05707526404827.561083302
#Sta/Elev= 30
       0 3211.57    29.3 3198.63    43.6 3190.26      49 3188.16    56.5 3187.38
      70 3183.55    75.8 3183.87    83.6 3186.02    86.5 3185.71    93.8 3181.08
    97.2 3180.69   114.2 3185.89   117.6 3184.64   131.2 3176.25   137.4 3175.33
   151.6 3175.24   168.7 3174.84   178.9 3175.41   182.3 3176.91   189.1 3181.73
   202.8 3187.97   216.5 3195.66   243.4 3212.47     254 3220.06   267.3 3227.56
   273.3 3231.76   288.2 3244.36   301.9 3250.79   315.5 3260.11   321.2 3262.69
#Mann= 5 ,-1 , 0
       0      .1       0   137.4    .045       0   151.6      .1       0
   243.4      .1       0   267.3      .1       0
Bank Sta=137.4,151.6
XS Rating Curve= 0 ,0
Exp/Cntr=0.3,0.1

Type RM Length L Ch R = 1 ,5281    ,92.1,91.7,92.4
XS GIS Cut Line= 2
2109123.34869927404555.6859708732109045.22352743404831.727741629
#Sta/Elev= 30
       0 3205.66     3.7 3204.34    17.7 3201.76    34.8 3199.41    55.2 3194.45
    65.4 3193.42    68.9 3192.22    89.3 3177.43    96.1 3174.22    99.5 3173.39
     103 3173.86   109.8 3176.18   113.2 3175.73   116.6  3172.7     120 3168.83
   123.4 3165.88   126.8 3165.24   130.2 3165.22   137.1 3166.09     147 3165.09
  153.263165.879     178 3170.24   192.4 3170.66   201.8 3171.65   215.5 3175.79
     227 3181.96   249.6 3196.65   266.8 3209.58   274.8 3214.02   286.9 3218.45
#Mann= 4 ,-1 , 0
       0      .1       0   137.1    .045       0  153.26      .1       0
  265.07      .1       0
Bank Sta=137.1,153.26
XS Rating Curve= 0 ,0
Exp/Cntr=0.3,0.1

Type RM Length L Ch R = 1 ,5190    ,151.9,148.2,136.9
XS GIS Cut Line= 2
2109036.99585609404538.5374624262108950.94396008404814.326735719
#Sta/Elev= 30
       0 3208.72     9.7 3205.03    35.8    3197    50.6 3191.62    63.3 3185.46
    77.1 3176.41    87.4 3171.72    97.7 3165.15   101.1 3163.49   104.6 3162.23
   113.4 3161.37   118.7 3160.19   128.6 3159.94   135.5 3160.03   145.8 3160.49
   156.1 3160.11   159.5 3160.95   165.8 3163.98   168.4 3164.28   177.5 3164.01
   190.5 3162.34   193.9 3162.36   197.3 3162.98   200.8 3164.31   211.1 3169.81
   228.3 3182.17   238.6  3187.6   252.3 3192.48   266.1 3195.44   288.9  3202.5
#Mann= 3 ,-1 , 0
       0      .1       0   118.7    .045       0   135.5      .1       0
Bank Sta=118.7,135.5
XS Rating Curve= 0 ,0
Exp/Cntr(USF)=0,0
Exp/Cntr=0.3,0.1

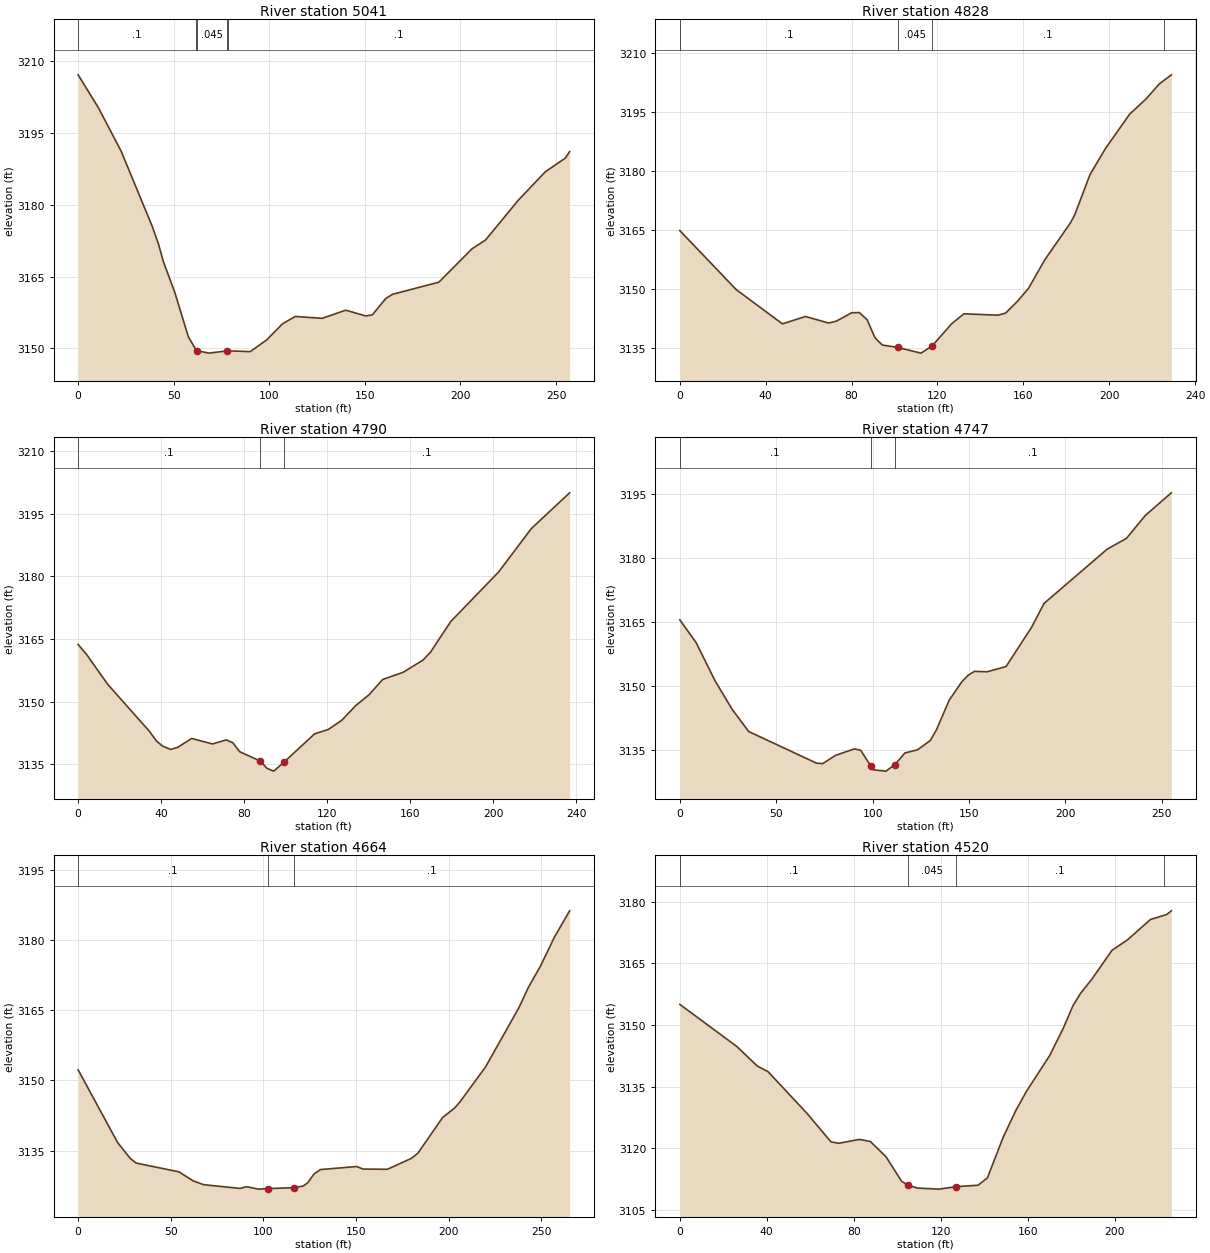
Type RM Length L Ch R = 1 ,5041    ,213.4,213,217.1
XS GIS Cut Line= 4
2108820.56877054 404574.183729432108857.76339603404619.990751407
2108907.04476208404684.2947532782108946.15920088404794.639307273
#Sta/Elev= 30
       0 3207.16    10.8 3200.15    22.5 3191.22    38.8 3175.49    42.1 3171.74
    44.6 3168.14    50.5  3161.8    57.7  3152.4    61.5 3149.82    62.1 3149.55
    68.4 3149.03      78  3149.5    78.5 3149.51      90 3149.34    98.7 3151.81
   106.9 3155.15   113.6 3156.69   127.7  3156.3     140    3158   150.4  3156.8
   153.9 3157.02   160.9 3160.43   164.4 3161.31   188.7 3163.85   206.1 3170.84
   213.1 3172.65   230.5 3181.08   244.4 3186.91   254.9 3189.78   257.1 3191.13
#Mann= 5 ,-1 , 0
       0      .1       0    61.5    .045       0    62.1    .045       0
      78    .045       0    78.5      .1       0
Bank Sta=62.1,78
XS Rating Curve= 0 ,0
Exp/Cntr=0.3,0.1

Type RM Length L Ch R = 1 ,4828    ,37.1,38.5,44.1
XS GIS Cut Line= 2
2108680.54085785404689.6932487932108772.30707851 404899.43593955
#Sta/Elev= 30
       0 3164.92    26.3  3149.9    47.8 3141.21    58.5 3143.09    69.3 3141.42
    72.9  3141.9      80 3144.03    83.6 3144.09    87.2 3142.27    90.8 3137.79
    92.5 3136.75    94.4 3135.82   101.5 3135.22   112.3 3133.77   117.4 3135.53
   126.6 3141.24   132.3 3143.77   148.1 3143.42   151.7 3143.94   157.2 3146.92
   162.4 3150.26   169.9 3157.44     182 3166.96   183.9 3168.91     191 3179.14
   198.2 3185.77   209.5 3194.54     217 3198.33   223.3 3202.22   228.9 3204.53
#Mann= 4 ,-1 , 0
       0      .1       0   101.5    .045       0   117.4      .1       0
  225.61      .1       0
Bank Sta=101.5,117.4
XS Rating Curve= 0 ,0
Exp/Cntr=0.3,0.1

Type RM Length L Ch R = 1 ,4790    ,43.3,43.2,43.2
XS GIS Cut Line= 3
2108670.83576852404693.455695881 2108685.2332382404753.616551346
2108682.14806613404928.442968939
#Sta/Elev= 30
       0 3163.71     4.1 3161.29    14.2 3154.19    34.4 3142.86    37.8 3140.54
    40.6 3139.38    44.5 3138.56    47.9 3139.04    54.7 3141.19    64.7 3139.87
    71.3 3140.84    74.5 3140.16    77.8 3138.01    87.7 3135.78    90.9 3134.05
    94.2 3133.36    99.3 3135.58   113.9 3142.29   120.5 3143.34     127 3145.55
   133.6 3149.01   140.2 3151.69   146.7 3155.32   156.6 3157.05   166.1 3159.96
   169.7 3161.85   179.5 3169.22   202.5 3181.05   218.3 3191.48   236.7 3200.02
#Mann= 3 ,-1 , 0
       0      .1       0    87.7    .045       0    99.3      .1       0
Bank Sta=87.7,99.3
XS Rating Curve= 0 ,0
Exp/Cntr(USF)=0,0
Exp/Cntr=0.3,0.1

Type RM Length L Ch R = 1 ,4747    ,83.8,83.1,82.1
XS GIS Cut Line= 2
2108641.15055069 404685.646595492108642.64994432404940.543512339
#Sta/Elev= 30
       0 3165.51     8.5 3160.15    18.3 3151.22    27.2 3144.54    35.7 3139.39
    70.8    3132    74.1 3131.87    80.7  3133.8    90.5 3135.32    93.8    3135
    98.93131.427   100.3 3130.44   106.9 3130.12   111.6 3131.66   116.7 3134.36
   123.3 3135.11   129.9 3137.29   133.1  3139.8   139.7 3146.71   146.3 3151.06
   149.6 3152.58   152.8 3153.46   159.4 3153.37   169.2 3154.59   182.4 3163.75
   188.9 3169.36   221.7 3182.08   231.6 3184.56   241.4 3189.93   254.9 3195.23
#Mann= 3 ,-1 , 0
       0      .1       0    98.9    .045       0   111.6      .1       0
Bank Sta=98.9,111.6
XS Rating Curve= 0 ,0
Exp/Cntr(USF)=0,0
Exp/Cntr=0.3,0.1

Type RM Length L Ch R = 1 ,4664    ,143.5,143.3,142.2
XS GIS Cut Line= 2
2108544.54309614404689.3818226842108579.96242481404952.403133764
#Sta/Elev= 30
       0 3152.27    21.3 3136.74      28  3133.4    31.3 3132.34    54.4 3130.47
    62.1 3128.54    67.7 3127.72    87.5 3126.92    90.9 3127.29    97.5 3126.77
   102.63126.888   116.43127.073   121.5 3127.42     124 3128.14   127.4 3130.01
   130.9 3130.95   150.4  3131.6   153.8 3131.06     167 3131.01   179.9 3133.33
   183.5 3134.46   196.8 3142.06   203.4 3144.14   206.2 3145.42     220 3152.88
   238.1  3165.6   243.1 3169.86   249.8 3174.54   257.2 3180.62   265.4 3186.24
#Mann= 3 ,-1 , 0
       0      .1       0   102.6    .045       0   116.4      .1       0
Bank Sta=102.6,116.4
XS Rating Curve= 0 ,0
Exp/Cntr(USF)=0,0
Exp/Cntr=0.3,0.1

Type RM Length L Ch R = 1 ,4520    ,133.1,136.1,142.2
XS GIS Cut Line= 3
2108400.43183804404778.6028478742108448.28410453404882.845093459
2108493.14031401404984.852763459
#Sta/Elev= 30
       0 3155.03    26.2 3144.79    35.6 3140.05    40.6 3138.65    58.7  3128.4
    69.5 3121.59    73.1 3121.23    82.6 3122.18    87.6 3121.68    94.8    3118
     102 3112.01   104.9 3111.05   109.2 3110.34   119.2 3110.08     127 3110.67
   137.2 3111.03   141.5 3112.82   148.7 3122.65   154.6 3129.25   159.4 3133.82
   170.2 3142.64   176.3 3149.12   180.9 3154.76   184.4 3157.76   189.5 3161.13
   198.8 3168.18     206 3170.76   216.5 3175.69   223.9 3176.88   226.1 3177.79
#Mann= 4 ,-1 , 0
       0      .1       0   104.9    .045       0     127      .1       0
  222.73      .1       0
Bank Sta=104.9,127
XS Rating Curve= 0 ,0
Exp/Cntr=0.3,0.1

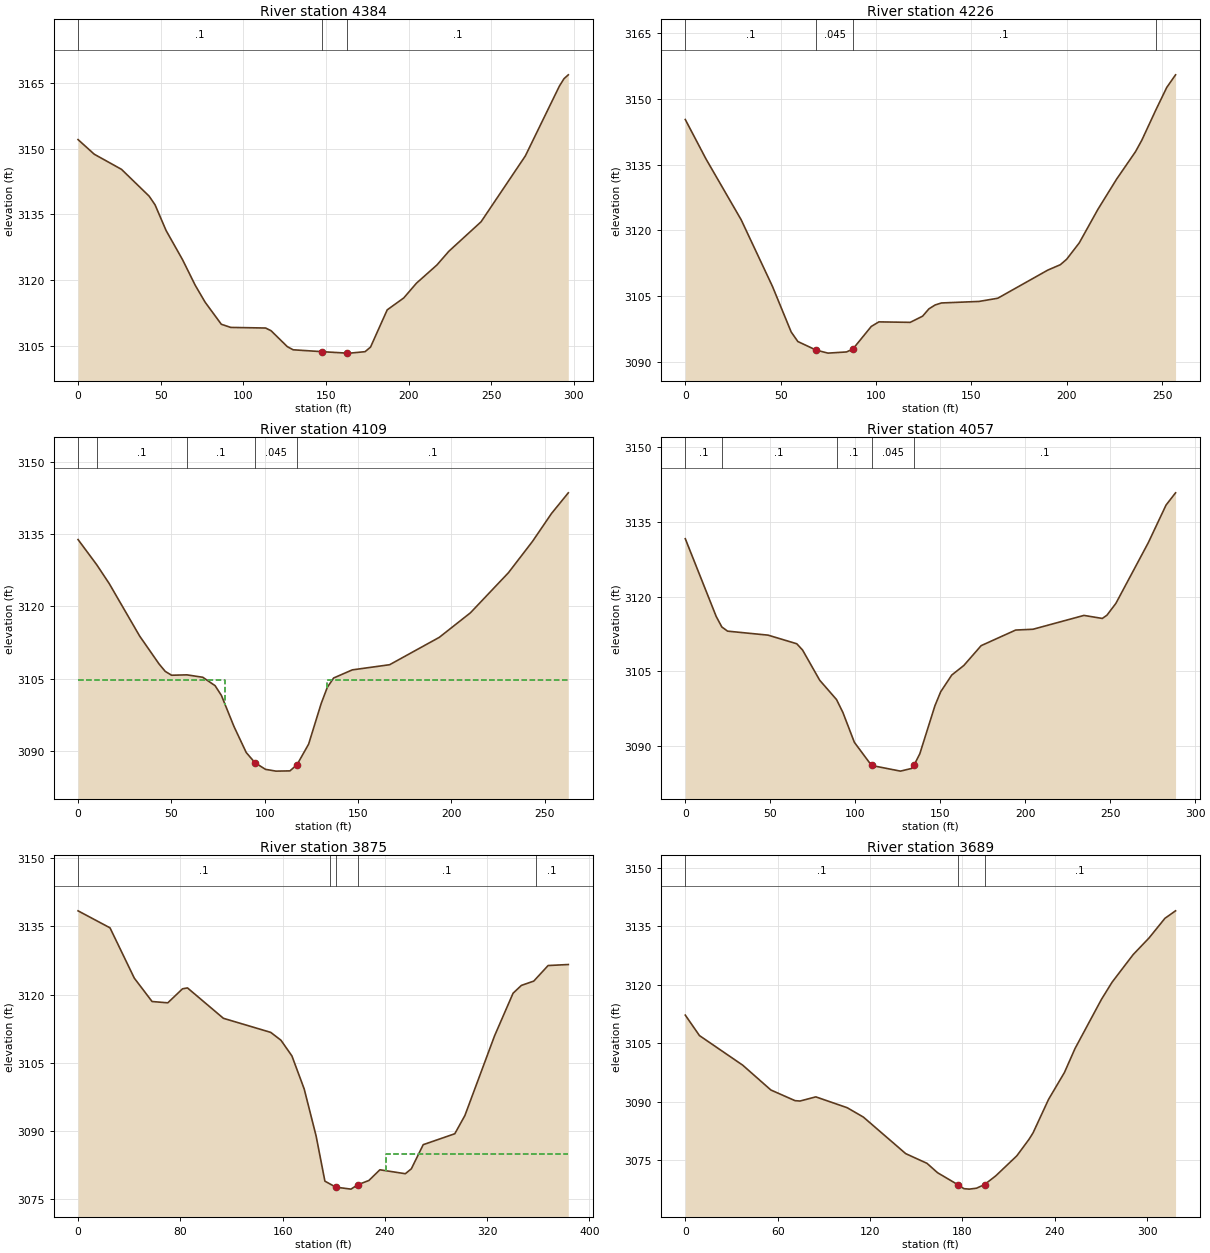
Type RM Length L Ch R = 1 ,4384    ,159.7,158.5,155.2
XS GIS Cut Line= 2
  2108353.290706404779.6764991372108295.43913583405070.705316409
#Sta/Elev= 30
       0 3152.03     9.8  3148.7    26.3 3145.25      43 3139.15    46.6 3137.17
    53.3  3131.3    63.3 3124.62    70.9 3118.84    76.9 3114.98    86.7 3109.95
    92.4 3109.23   113.5 3109.09   116.8 3108.48   126.7 3104.83   130.2 3104.13
   147.73103.701   162.63103.373   164.6 3103.37   173.7  3103.7     177 3104.74
   187.1 3113.23   197.1 3115.94   204.8 3119.31   217.2 3123.46   224.4 3126.58
   243.9  3133.3   270.7 3148.31   291.3 3164.22   294.1 3165.91   296.7 3166.79
#Mann= 3 ,-1 , 0
       0      .1       0   147.7    .045       0   162.6      .1       0
Bank Sta=147.7,162.6
XS Rating Curve= 0 ,0
Exp/Cntr(USF)=0,0
Exp/Cntr=0.3,0.1

Type RM Length L Ch R = 1 ,4226    ,117.9,117.1,114.2
XS GIS Cut Line= 3
2108179.62749033404809.2468349322108177.91350585404842.210756922
2108175.12035941405066.168970415
#Sta/Elev= 30
       0 3145.31    10.8 3136.34    29.3  3122.4    45.7 3107.18    55.5 3096.78
      59 3094.59    68.6 3092.63    74.8 3091.94    84.5 3092.21    87.8 3092.85
    97.5 3098.04   101.5 3099.08   117.9 3098.97   124.4 3100.38   127.7 3102.05
     131 3102.95   134.3  3103.4     154 3103.75   163.8 3104.48     190  3110.9
   196.6 3112.14   199.9 3113.38   206.5 3117.11   216.3 3124.79   226.1 3131.69
     236 3137.96   239.3 3140.57   246.6 3147.43   252.4 3152.65     257 3155.52
#Mann= 4 ,-1 , 0
       0      .1       0    68.6    .045       0    87.8      .1       0
   246.6      .1       0
Bank Sta=68.6,87.8
XS Rating Curve= 0 ,0
Exp/Cntr=0.5,0.3

Type RM Length L Ch R = 1 ,4109    ,52.1,51.6,50.7
XS GIS Cut Line= 4
 2108047.3068881404805.6861270522108059.57818902  404870.4192653
2108078.01122302 404968.006012382108094.18179435405064.019271791
#Sta/Elev= 30
       0 3133.85      10 3128.64    16.7 3124.73      33 3113.86    43.4 3108.08
    46.7 3106.55    50.1 3105.75    58.3 3105.83    66.8 3105.33    73.4 3103.59
    76.8 3101.56    83.5 3095.15    90.1 3089.73    94.8 3087.62   100.4 3086.26
     106 3085.89   113.5 3085.94   117.3 3087.23   123.5 3091.48   130.2 3099.86
   133.5 3103.23   136.9 3105.18   146.9 3106.86   166.9 3107.93   193.5  3113.6
   210.2 3118.69   230.5 3126.97   243.4 3133.46   253.6 3139.25   262.6 3143.53
#Mann= 5 ,-1 , 0
       0      .1       0      10      .1       0    58.3      .1       0
    94.8    .045       0   117.3      .1       0
#XS Ineff= 2 , 0
            78.8 3104.75   133.3         3104.75
Permanent Ineff=
       F       F
Bank Sta=94.8,117.3
XS Rating Curve= 0 ,0
Exp/Cntr=0.5,0.3

Type RM Length L Ch R = 1 ,4057    ,185,182.1,173.9
XS GIS Cut Line= 3
2107987.93200687404807.7694562082108027.04938269404959.331489041
 2108060.8485277405086.936220706
#Sta/Elev= 30
       0 3131.64    18.2 3116.03    21.5 3113.93    24.9 3113.09    48.7 3112.29
    65.6 3110.56      69 3109.31    79.1 3103.24      89 3099.36    92.7 3096.81
    99.5 3090.78   109.6 3086.14   126.6    3085   133.4 3085.56   134.7 3086.26
     138 3088.48   146.9 3098.12   150.3 3100.93   156.8 3104.28   163.9  3106.2
   174.1 3110.18   194.4 3113.31   204.6 3113.47   234.6 3116.25   245.4 3115.64
   248.1 3116.28   253.4 3118.67   272.5 3130.87   282.9 3138.39   288.5 3140.85
#Mann= 5 ,-1 , 0
       0      .1       0    21.5      .1       0      89      .1       0
   109.6    .045       0   134.7      .1       0
Bank Sta=109.6,134.7
XS Rating Curve= 0 ,0
Exp/Cntr=0.5,0.3

Type RM Length L Ch R = 1 ,3875    ,181.1,186.4,190.8
XS GIS Cut Line= 3
2107687.93195069404868.1860020462107821.51557467404949.023092226
2107994.93760629 405096.02847348
#Sta/Elev= 30
       0 3138.39      25 3134.65      44  3123.6    57.9 3118.46    70.2 3118.17
    81.7 3121.25    85.6 3121.45   113.7 3114.77   150.7 3111.68   158.7 3109.96
   167.3  3106.5   176.9 3099.24   186.2 3088.93   193.1 3078.98   201.7 3077.66
   213.5 3077.23   218.9  3078.2   227.5 3079.13   236.1 3081.48     256 3080.62
   260.7 3081.69     270    3087   294.7  3089.4   302.6  3093.4   325.8 3110.91
   340.3 3120.29   346.8    3122   356.5 3122.95   367.7 3126.37   383.5 3126.59
#Mann= 5 ,-1 , 0
       0      .1       0  196.78      .1       0   201.7    .045       0
   218.9      .1       0  358.04      .1       0
#XS Ineff= 2 , 0
                          240.57         3084.95
Permanent Ineff=
       F       F
Bank Sta=201.7,218.9
XS Rating Curve= 0 ,0
Exp/Cntr=0.3,0.1

Type RM Length L Ch R = 1 ,3689    ,174.5,175.7,177.5
XS GIS Cut Line= 2
2107677.32887616404924.8305366132107772.15837906405228.911917794
#Sta/Elev= 30
       0 3112.23     9.2 3106.99    37.3 3099.41    55.6 3093.05    71.3 3090.32
    74.5 3090.22    84.8 3091.29   105.2 3088.51   115.7 3086.11   143.2 3076.75
     157 3074.27   163.9 3071.86   176.93068.837     181 3067.78   184.5 3067.66
   189.2  3067.9   194.4 3068.83   201.7 3071.06   215.4  3076.2   223.3 3080.42
   225.9 3082.05     236 3090.65   246.3 3097.52   253.2 3103.68   270.4 3116.29
   277.3 3120.68     291 3127.75   301.3    3132   311.6 3137.02   318.5 3138.94
#Mann= 3 ,-1 , 0
       0      .1       0   176.9    .045       0   194.4      .1       0
Bank Sta=176.9,194.4
XS Rating Curve= 0 ,0
Exp/Cntr(USF)=0,0
Exp/Cntr=0.3,0.1