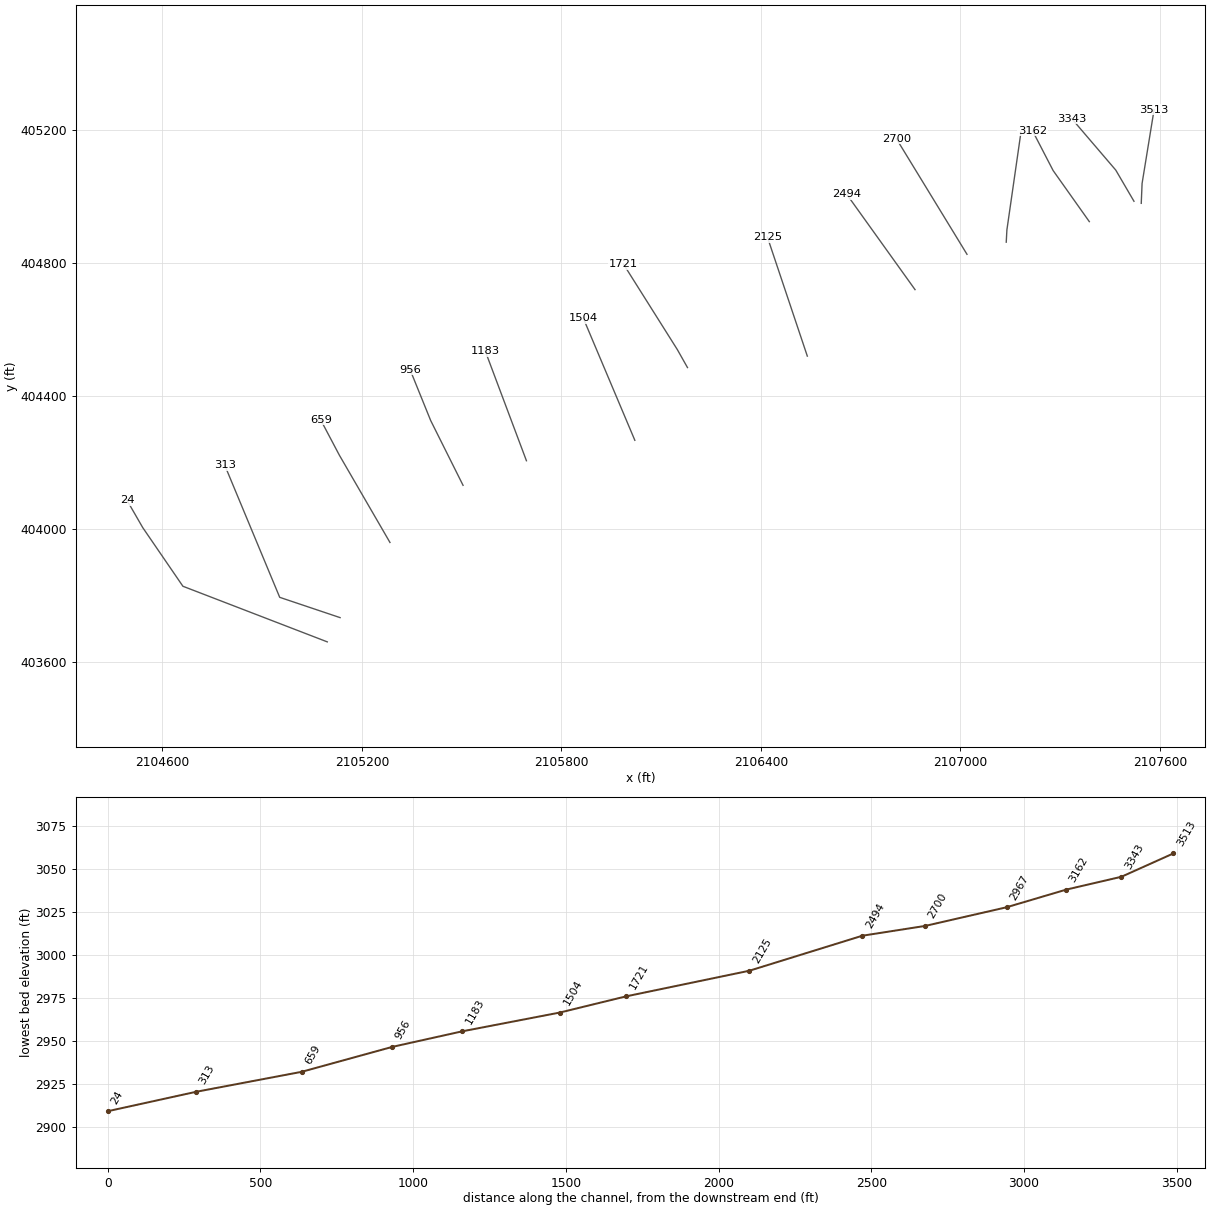
HEC-RAS study COLDSPRBR.prj: COLDSPRBR

--- COLDSPRBR.g01 (geometry) --- (continued)

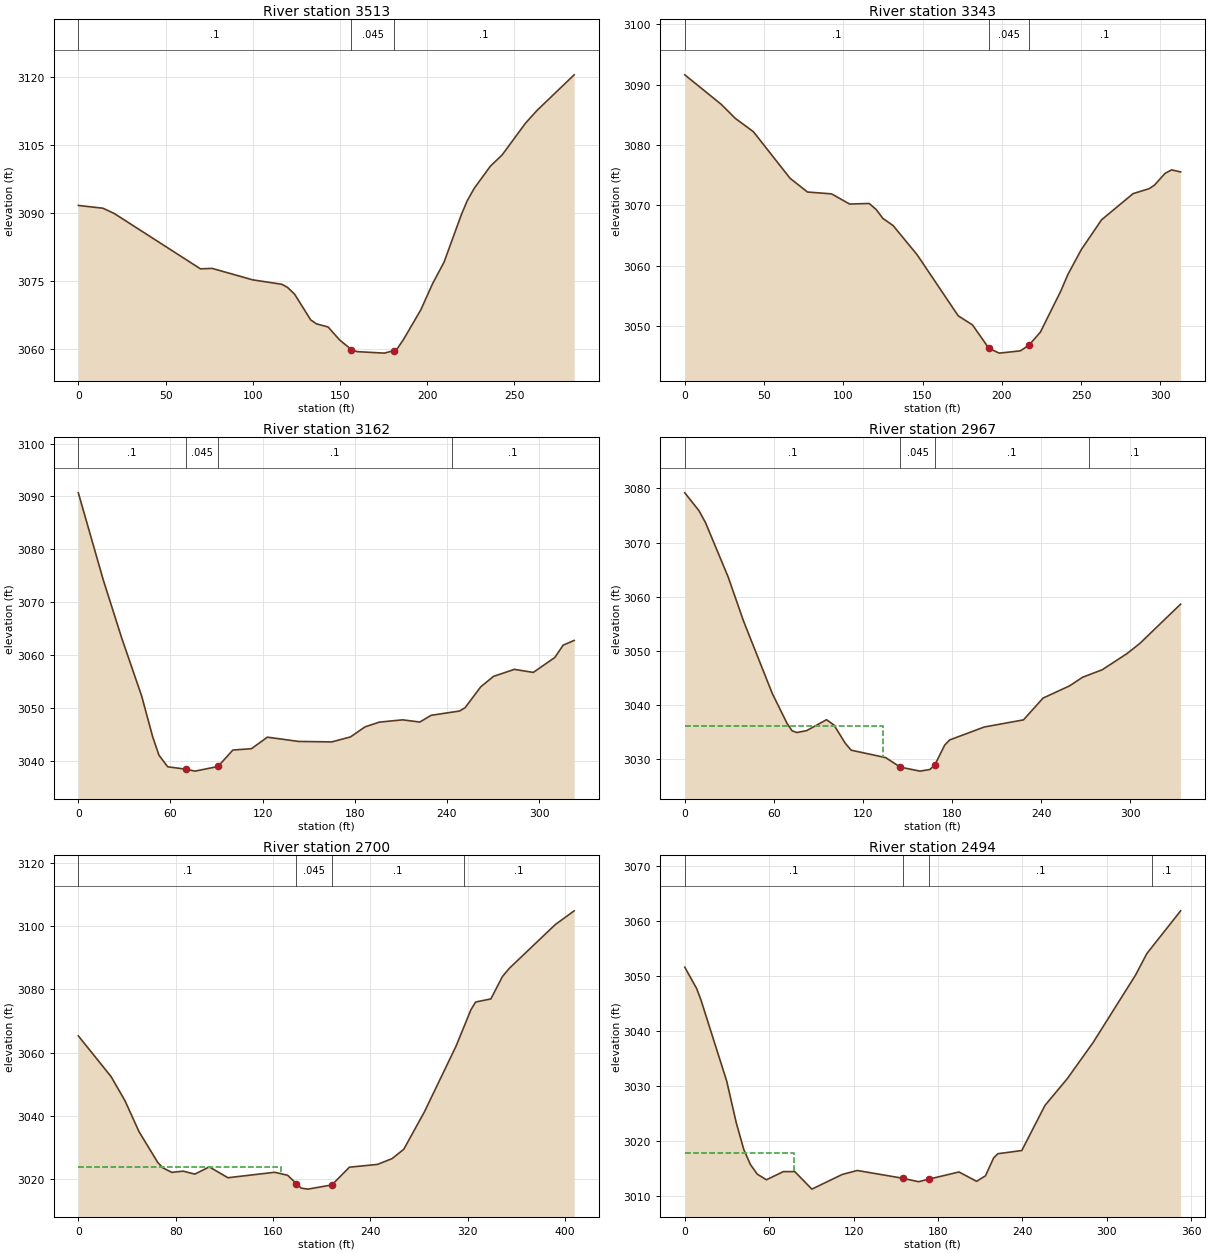
Type RM Length L Ch R = 1 ,3513    ,160.9,170.2,182.2
XS GIS Cut Line= 3
 2107544.1819101404978.6027759612107546.70683944405038.485202134
2107582.72349969 405259.85286963
#Sta/Elev= 30
       0 3091.68    14.1 3091.07    20.7 3089.88      70 3077.67    76.7 3077.77
    99.9 3075.24   116.6 3074.26   119.9 3073.57     124 3072.05   133.2 3066.38
   136.5 3065.51   143.2 3064.81   149.8 3061.94   156.5 3059.84   159.8 3059.37
   175.4 3059.04   181.1 3059.62     183 3060.13   186.4 3062.07   196.3  3068.6
     203 3074.35   209.6 3079.12   219.6  3089.7   222.9 3092.72   226.9 3095.45
   236.2 3100.37   242.9 3102.83   256.2 3109.81   262.8 3112.64   284.2 3120.55
#Mann= 3 ,-1 , 0
       0      .1       0   156.5    .045       0   181.1      .1       0
Bank Sta=156.5,181.1
XS Rating Curve= 0 ,0
Exp/Cntr=0.3,0.1

Type RM Length L Ch R = 1 ,3343    ,178.1,181,177.8
XS GIS Cut Line= 3
2107522.30695385404984.8527634592107467.55312636405078.603888288
2107334.80700079405233.810926959
#Sta/Elev= 30
       0 3091.64      23 3086.74    31.9 3084.41    43.3  3082.2    66.4 3074.48
    77.4  3072.2    92.6 3071.89     104  3070.2   116.3  3070.3   120.7 3069.31
     125 3067.81   131.4 3066.64   146.6 3061.78   172.5 3051.66   181.5 3050.15
   191.9 3046.25   198.4 3045.47   211.7 3045.85  217.09 3046.79   224.3 3048.94
   237.3 3055.82   241.6 3058.48   250.2 3062.67   262.9 3067.58   282.8 3071.93
   292.9 3072.75   296.3 3073.34     303  3075.3   307.1 3075.87   312.8 3075.53
#Mann= 3 ,-1 , 0
       0      .1       0   191.9    .045       0  217.09      .1       0
Bank Sta=191.9,217.09
XS Rating Curve= 0 ,0
Exp/Cntr=0.3,0.1

Type RM Length L Ch R = 1 ,3162    ,198.6,194.9,182.6
XS GIS Cut Line= 3
2107387.97951268404923.681768653 2107279.1629023405077.244828917
2107217.25487499405196.771106241
#Sta/Elev= 30
       0 3090.68    16.2 3074.23    28.3 3063.14    41.2 3052.24    48.4  3044.5
    52.5 3041.01    58.2 3038.81      703038.355      76 3037.99   90.923038.871
   100.6 3041.98   112.7 3042.24   123.1 3044.42   143.4 3043.61     165 3043.52
   177.2 3044.47   186.6 3046.36     196 3047.27   211.2  3047.7   222.3 3047.28
   229.7 3048.56   248.2 3049.37   251.8    3050     262 3053.96   270.3 3055.93
   283.9 3057.26   296.2 3056.68   310.2  3059.5   315.6 3061.83   322.8 3062.74
#Mann= 4 ,-1 , 0
       0      .1       0      70    .045       0   90.92      .1       0
  243.18      .1       0
Bank Sta=70,90.92
XS Rating Curve= 0 ,0
Exp/Cntr=0.3,0.1

Type RM Length L Ch R = 1 ,2967    ,260.4,266.6,278
XS GIS Cut Line= 3
2107138.13810277404861.8346367932107140.09610412404898.611138046
 2107182.4090116405192.563962206
#Sta/Elev= 30
       0 3079.18     9.5  3075.9    13.9  3073.7    29.2 3063.63    39.6 3055.44
    58.9  3042.1    68.9 3036.54    72.2 3035.21    75.5 3034.88    82.1 3035.24
    95.4 3037.25   100.5 3036.25     108 3032.91     112 3031.62   135.2 3030.25
   145.1 3028.49   158.3 3027.75     165 3028.05   168.3 3028.89     175 3032.57
   178.3 3033.51   201.5  3035.9     228 3037.22   241.2 3041.25     259  3043.5
   267.8  3045.1     281 3046.48   297.6 3049.45   306.2 3051.31   333.8 3058.61
#Mann= 4 ,-1 , 0
       0      .1       0   145.1    .045       0   168.3      .1       0
  272.42      .1       0
#XS Ineff= 2 , 0
           133.7 3036.06
Permanent Ineff=
       F       F
Bank Sta=145.1,168.3
XS Rating Curve= 0 ,0
Exp/Cntr=0.3,0.1

Type RM Length L Ch R = 1 ,2700    ,205,205.8,209
XS GIS Cut Line= 2
2107020.08256459404825.3763763762106807.58266151 405173.29300338
#Sta/Elev= 30
       0 3065.32    26.9 3052.47    38.4 3044.81    49.9 3035.07    65.3 3025.34
    69.5 3023.62    76.9  3022.2    86.2 3022.59    95.8 3021.65   107.7 3023.94
     123 3020.51   161.4 3022.23   172.1 3021.29   179.3 3018.65   183.3 3017.22
   188.8 3016.91   208.5 3018.24   222.9 3023.84     246 3024.72     258 3026.55
   267.6  3029.5   284.5 3041.26   310.6 3062.09   322.9 3073.65   326.7 3076.02
   339.2 3076.99   348.7 3084.05   354.2 3086.59   392.1 3100.45   407.7 3104.82
#Mann= 4 ,-1 , 0
       0      .1       0   179.3    .045       0   208.5      .1       0
  317.11      .1       0
#XS Ineff= 2 , 0
          166.69 3023.97
Permanent Ineff=
       F       F
Bank Sta=179.3,208.5
XS Rating Curve= 0 ,0
Exp/Cntr=0.3,0.1

Type RM Length L Ch R = 1 ,2494    ,371,369.8,365.3
XS GIS Cut Line= 2
2106863.83254904404719.1265888812106658.62429804405005.584677383
#Sta/Elev= 30
       0 3051.57     8.5 3047.66    11.5 3045.61    29.8 3030.85    36.6 3023.26
      42 3018.36    46.7 3015.66    51.5 3013.94      58 3012.91    70.1  3014.4
    78.2 3014.39    90.3 3011.21     112 3013.89   122.6  3014.6   154.9 3013.19
   154.9 3013.18   166.2 3012.56   173.7 3013.04   194.9 3014.33   207.4 3012.63
   213.7 3013.63   219.5 3016.89   222.5 3017.65   239.5 3018.23     256 3026.44
   271.9 3031.32   290.2 3037.88   320.4 3050.16   328.4 3054.06   352.4 3061.83
#Mann= 4 ,-1 , 0
       0      .1       0   154.9    .045       0   173.7      .1       0
  332.16      .1       0
#XS Ineff= 2 , 0
           77.33 3017.75
Permanent Ineff=
       F       F
Bank Sta=154.9,173.7
XS Rating Curve= 0 ,0
Exp/Cntr=0.3,0.1

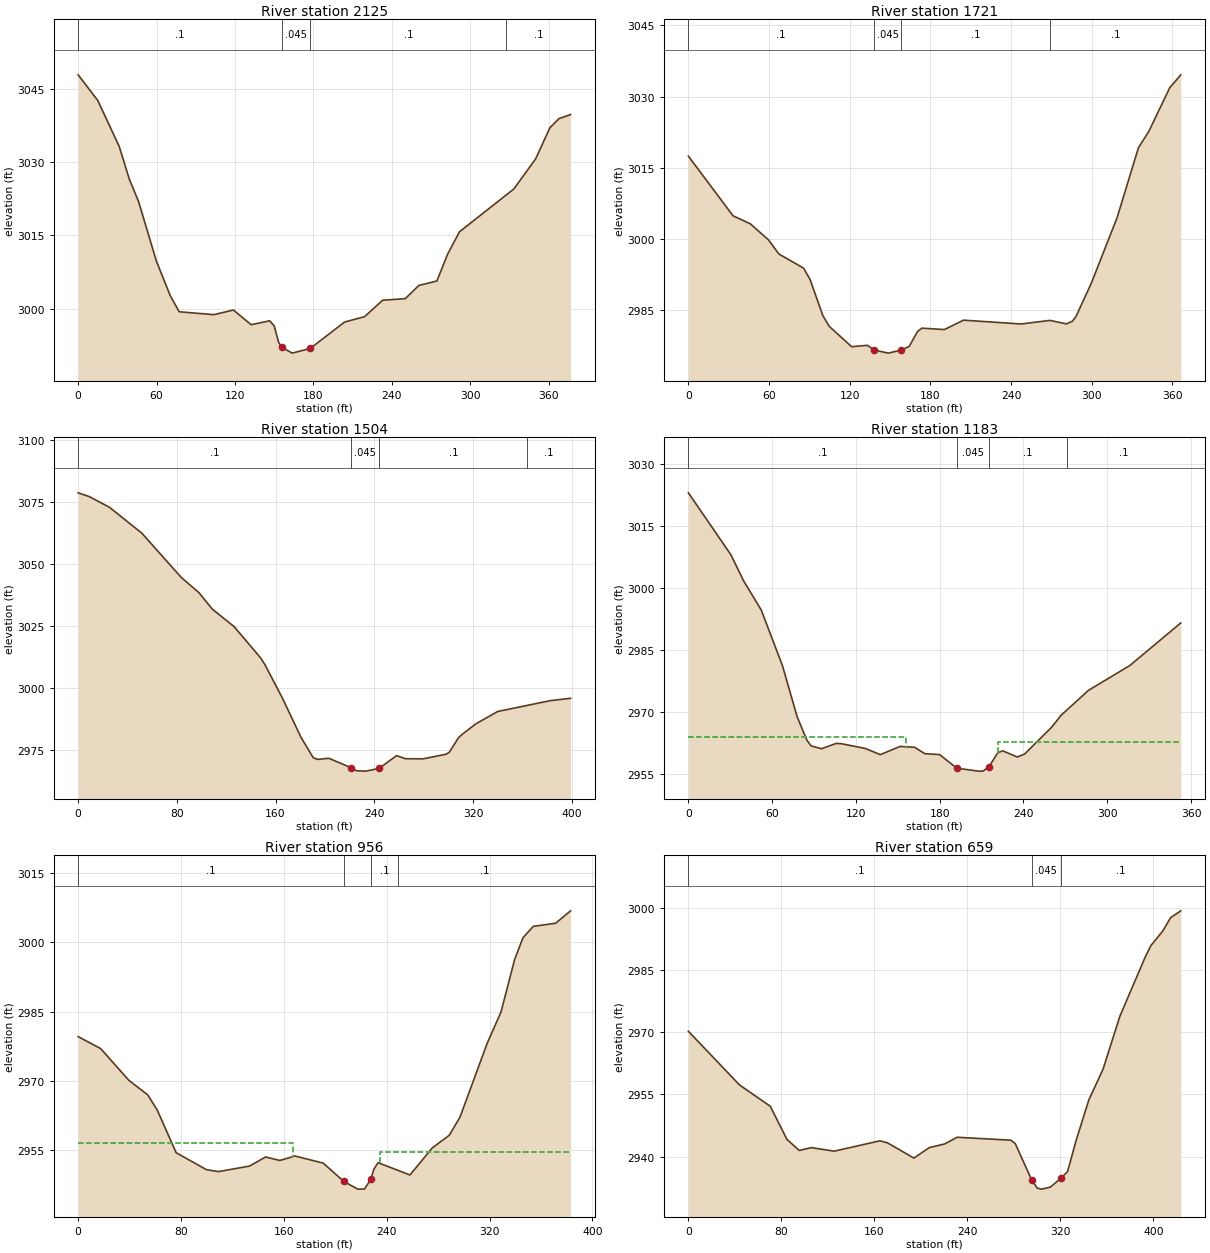
Type RM Length L Ch R = 1 ,2125    ,401.8,403.2,405.7
XS GIS Cut Line= 2
2106539.87420744404519.1263327152106420.08245227404876.418269038
#Sta/Elev= 30
       0 3047.87      15 3042.62    31.4 3033.22    39.2 3026.46    46.2 3021.94
    59.9 3009.69    70.4 3002.69    77.3 2999.34   103.9 2998.75   118.8  2999.7
   132.4 2996.69   146.5 2997.49     150 2996.47   153.4  2993.1   155.7 2992.09
   163.8 2990.87   177.6 2991.83   203.9 2997.24   219.2 2998.34     233  3001.7
   250.3 3002.03   260.7 3004.73   274.5 3005.64   282.7 3011.12   291.8 3015.72
   333.4 3024.49   350.1 3030.66     361 3037.04     368 3038.91   376.8 3039.73
#Mann= 4 ,-1 , 0
       0      .1       0   155.7    .045       0   177.6      .1       0
  327.66      .1       0
Bank Sta=155.7,177.6
XS Rating Curve= 0 ,0
Exp/Cntr=0.3,0.1

Type RM Length L Ch R = 1 ,1721    ,220.1,216.9,215.9
XS GIS Cut Line= 3
2106179.45760545404484.7514014542106149.05051401404538.624981374
2105986.74932945404796.209768042
#Sta/Elev= 30
       0 3017.45    33.2  3004.9    46.1  3003.2    59.6 2999.83    67.3 2996.86
    85.7 2993.88    90.5  2991.5     100  2983.9   104.8 2981.62   121.4 2977.35
   133.2 2977.63   138.1 2976.65   148.7 2975.99  158.412976.642   164.3 2977.42
   170.4 2980.53   173.7 2981.25   190.4 2980.95   204.7 2982.93   247.5 2982.12
   268.9 2982.88   281.2 2982.14   285.6  2982.7   288.3 2983.67   299.8 2990.75
   318.9 3004.49   334.8 3019.22   342.6 3022.71   358.1 3031.86   366.3 3034.57
#Mann= 4 ,-1 , 0
       0      .1       0   138.1    .045       0  158.41      .1       0
  269.09      .1       0
Bank Sta=138.1,158.41
XS Rating Curve= 0 ,0
Exp/Cntr=0.3,0.1

Type RM Length L Ch R = 1 ,1504    ,321.7,321,320.9
XS GIS Cut Line= 2
2106021.12426069404266.0015108732105865.91590968404633.709764957
#Sta/Elev= 30
       0 3078.55     8.9 3077.05    25.4 3072.74    51.6 3062.32    83.7 3044.44
    97.9 3038.39   108.6 3031.82   126.4 3024.73   147.8  3012.2   151.3 3009.49
   165.6 2995.93   180.6 2980.21   190.5 2972.01     194 2971.31   203.2 2971.75
   220.92968.038   225.7 2966.72   233.2 2966.59   243.9 2967.69   258.1 2972.83
   265.3 2971.58   279.5 2971.53   298.3  2973.4   300.9 2974.22   308.3 2980.08
   310.9 2981.22   322.2 2985.57   340.1 2990.59   382.8 2994.96   399.1 2995.89
#Mann= 4 ,-1 , 0
       0      .1       0   220.9    .045       0   243.9      .1       0
  364.15      .1       0
Bank Sta=220.9,243.9
XS Rating Curve= 0 ,0
Exp/Cntr=0.3,0.1

Type RM Length L Ch R = 1 ,1183    ,226.5,227.6,227.8
XS GIS Cut Line= 2
2105695.08258995404204.5429723712105571.12417644404534.751301467
#Sta/Elev= 30
       0 3023.01    30.5 3007.98    39.5 3001.73    52.2 2994.62    67.4 2981.13
    77.9 2968.78    84.9  2963.1    87.9 2961.73    95.4 2961.04   105.9 2962.34
   109.4 2962.27   126.9 2961.09   137.5 2959.61   151.6  2961.6     162  2961.4
   169.4 2959.84   179.9 2959.63   192.3 2956.33   207.6 2955.62     211 2955.62
   215.3 2956.69   221.6 2960.06   225.1 2960.54   235.6 2959.04   240.8 2959.75
   260.1 2966.22   267.1 2969.19   286.6 2975.19   316.2 2981.19   352.7 2991.51
#Mann= 4 ,-1 , 0
       0      .1       0   192.3    .045       0   215.3      .1       0
  271.29      .1       0
#XS Ineff= 2 , 0
          155.52 2963.87  221.62         2962.56
Permanent Ineff=
       F       F
Bank Sta=192.3,215.3
XS Rating Curve= 0 ,0
Exp/Cntr=0.3,0.1

Type RM Length L Ch R = 1 ,956     ,296.4,297,298.7
XS GIS Cut Line= 3
2105504.45764312404130.5847869662105407.11597428404325.381969541
2105345.08263376404478.501413956
#Sta/Elev= 30
       0 2979.58    17.5 2976.99    39.5 2970.12    54.2 2966.98    61.5 2963.72
    76.2 2954.51    99.7 2950.84   109.2 2950.42   133.3 2951.61   145.8 2953.58
   156.9 2952.82   168.6 2953.79   190.6 2952.25   206.7 2948.28   217.5 2946.63
   222.7 2946.65   227.6 2948.71   230.1 2950.99   233.3 2952.34   258.1 2949.69
   275.4 2955.52   288.6 2958.25     297 2962.17   318.2 2978.17   328.9 2984.89
   339.5 2996.23     346 3000.94     354 3003.39   371.4 3004.07     383 3006.75
#Mann= 4 ,-1 , 0
       0      .1       0   206.7    .045       0   227.6      .1       0
  248.81      .1       0
#XS Ineff= 2 , 0
          166.84 2956.62  234.52         2954.69
Permanent Ineff=
       F       F
Bank Sta=206.7,227.6
XS Rating Curve= 0 ,0
Exp/Cntr=0.3,0.1

Type RM Length L Ch R = 1 ,659     ,347.9,345.6,345
XS GIS Cut Line= 3
2105284.66575986403958.7098026282105132.58699578404221.013083801
2105076.33251512404327.459721297
#Sta/Elev= 30
       0 2970.26      44 2957.29    70.4 2952.16    84.8 2944.14    95.4 2941.47
   105.8 2942.16   125.4  2941.3   164.7  2943.8   171.2 2943.32     194 2939.63
   207.2 2942.16   220.5 2943.05   231.2 2944.66   277.4 2943.95   281.2 2943.13
   295.5 2934.24   300.2 2932.35     304 2932.13   311.4 2932.62  320.322934.721
   326.2 2936.38   333.6 2943.94   344.5 2953.69   356.7 2961.09   371.2  2973.9
     393 2988.19   397.9 2990.97   407.9  2994.4   414.9 2997.73   423.6 2999.36
#Mann= 3 ,-1 , 0
       0      .1       0   295.5    .045       0  320.32      .1       0
Bank Sta=295.5,320.32
XS Rating Curve= 0 ,0
Exp/Cntr=0.3,0.1

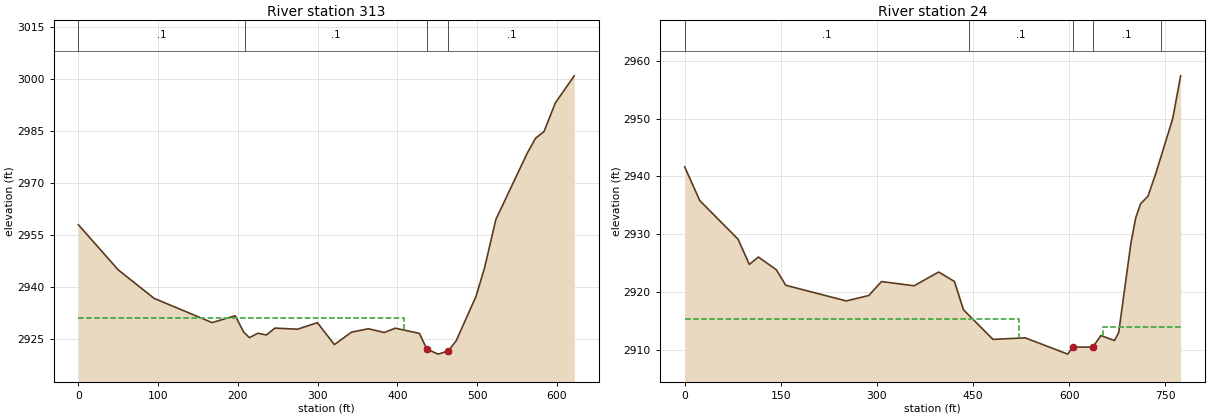
Type RM Length L Ch R = 1 ,313     ,287.5,289.3,290.5
XS GIS Cut Line= 3
2105134.66573179403732.6682599632104953.07324719403793.714397714
2104787.79076937 404191.00133279
#Sta/Elev= 30
       0 2957.88      50 2944.84      95 2936.62   167.7 2929.62   196.7 2931.59
   207.4 2926.87   214.5 2925.27   225.1 2926.54   235.8 2926.05   246.5 2928.03
   274.9 2927.72   299.8 2929.59   321.1 2923.26   342.4 2926.85   363.7 2927.84
   383.7 2926.76   397.4    2928   427.7 2926.51   437.1 2921.92   451.4 2920.52
     464 2921.46   473.9  2924.4   498.8 2937.26   509.4 2945.43   523.6 2959.39
   562.7 2978.42   573.4 2982.84     584 2984.77   598.2 2993.05   621.9 3000.84
#Mann= 4 ,-1 , 0
       0      .1       0  208.39      .1       0   437.1    .045       0
     464      .1       0
#XS Ineff= 2 , 0
          408.83 2930.93
Permanent Ineff=
       F       F
Bank Sta=437.1,464
XS Rating Curve= 0 ,0
Exp/Cntr=0.3,0.1

Type RM Length L Ch R = 1 ,24      ,37.63,24,51.19
XS GIS Cut Line= 4
 2105096.1241422403659.7514110512104661.94071025 403827.01416311
2104541.10892197 404003.402950042104493.83947867404085.429560352
#Sta/Elev= 30
       0 2941.66    23.6 2935.81    83.3 2929.14   100.9 2924.77     115 2926.05
   143.1 2923.84   157.7 2921.16   252.1 2918.45   287.3 2919.39   307.1 2921.81
   357.8 2921.07   396.3 2923.45   420.9 2921.82   434.9 2916.94     481 2911.79
   531.3 2912.06   597.7 2909.24   605.6 2910.49   606.1 2910.47   636.8 2910.45
   649.4 2912.46   670.6 2911.59   677.2 2912.98   696.3 2928.48   703.8 2932.87
   711.4 2935.28   722.8 2936.56   735.2 2940.56   761.5 2950.01   773.8 2957.42
#Mann= 5 ,-1 , 0
       0      .1       0   443.3      .1       0   605.6    .045       0
   636.8      .1       0   743.5      .1       0
#XS Ineff= 2 , 0
          521.11  2915.4  652.86         2913.87
Permanent Ineff=
       F       F
Bank Sta=606.1,636.8
XS Rating Curve= 0 ,0
Exp/Cntr=0.3,0.1
LCMann Table=0

Chan Stop Cuts=-1
Use User Specified Reach Order=0
Composite Channel Slope=5